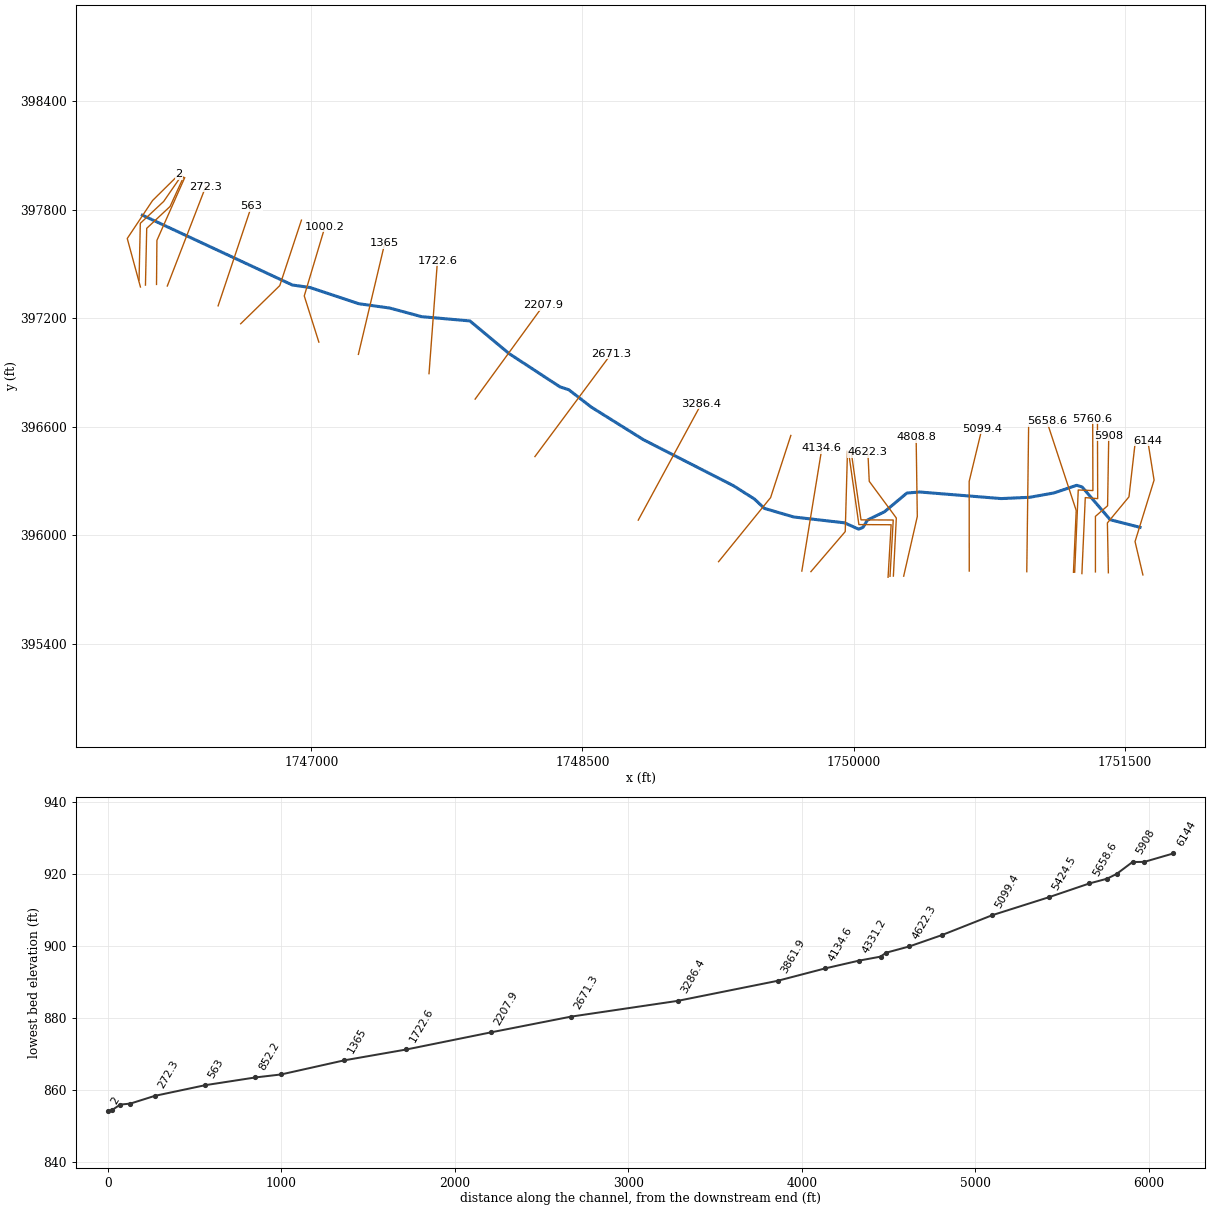
--- LFROCKCK.prj (project) ---

Proj Title=LFROCKCK
Current Plan=p01
Default Exp/Contr=0,0
English Units
Geom File=g01
Flow File=f01
Plan File=p01
BEGIN DESCRIPTION:
END DESCRIPTION:
DSS Export Rating Curves= 0
DSS Export Rating Curve Sorted= 0
DSS Export Volume Flow Curves= 0
DXF OffsetX= 0
DXF OffsetY= 0
DXF ScaleX= 0
DXF ScaleY= 0

--- LFROCKCK.p01 (plan) ---

Plan Title=Floodplain
Program Version=4.00
Geom File=g01
Flow File=f01
K Sum by GR=0
Std Step Tol=0.01
Critical Tol=0.01
Num of Std Step Trials=20
Max Error Tol=0.3
Flow Tol Ratio=0.001
Split Flow NTrial=30
Split Flow Tol=0.02
Split Flow Ratio=0.02
Log Output Level=0
Friction Slope Method=1
Unsteady Friction Slope Method=2
Unsteady Bridges Friction Slope Method=1
Global Log Level=0
CheckData=False
Run HTab=0
Run UNet=0
Run PostProcess=0
UNET Theta=0
UNET Theta Warmup=0
UNET ZTol=0
UNET ZSATol=0
UNET MxIter=0
UNET MaxInSteps=0
UNET DtIC=0
UNET DtMin=0
UNET MaxCRTS=0
UNET WFStab=0
UNET SFStab=0
UNET WFX=0
UNET SFX=0
UNET DSS MLevel=0
UNET DZMax Abort=0
UNET Convert EG Bridges=0
UNET Use Existing IB Tables=0
UNET Froude Limit=0
UNET Froude Power=0
Write IC File=0
Echo Input=False
Echo Output=False
Write Detailed=0

--- LFROCKCK.f01 (steady flow) ---

Flow Title=NFF Regression Equation
Program Version=4.00
Number of Profiles=1
Profile Names=P100yr
River Rch & RM=LFROCKCK,Main      ,6144
832.3084
River Rch & RM=LFROCKCK,Main      ,5975.4
832.3084
River Rch & RM=LFROCKCK,Main      ,5658.6
 999.636
River Rch & RM=LFROCKCK,Main      ,3861.9
1087.410
River Rch & RM=LFROCKCK,Main      ,563
1197.959
River Rch & RM=LFROCKCK,Main      ,272.3
1204.551
Boundary for River Rch & Prof#=LFROCKCK,Main      ,1
Up Type=0
Dn Type=3
Dn Slope=0.01009

--- LFROCKCK.g01 (geometry) ---

Geom Title=USGS 10m DEM
Program Version=5.03

River Reach=LFROCKCK        ,Main
Reach XY= 30
      1751584.35      396045.014     1751419.707      396087.066
      1751264.33      396268.102     1751234.537      396277.368
     1751109.095      396235.316       1750975.1      396211.083
     1750816.587      396203.956     1750365.564      396240.305
     1750295.003      396234.603     1750171.272      396131.256
     1750076.964      396085.343     1750051.531      396044.302
     1750028.011      396035.036     1749949.609       396069.96
      1749669.36      396102.033     1749506.142      396149.787
     1749452.117      396201.104     1749335.227      396275.229
     1748838.447      396528.965     1748548.504      396710.001
     1748424.732      396805.591     1748375.495       396821.72
     1748093.825      397005.935     1747877.521      397186.075
     1747609.772      397209.844     1747434.047      397257.384
     1747263.415      397281.153     1746992.016      397371.139
     1746895.239      397384.721      1746065.56      397770.862

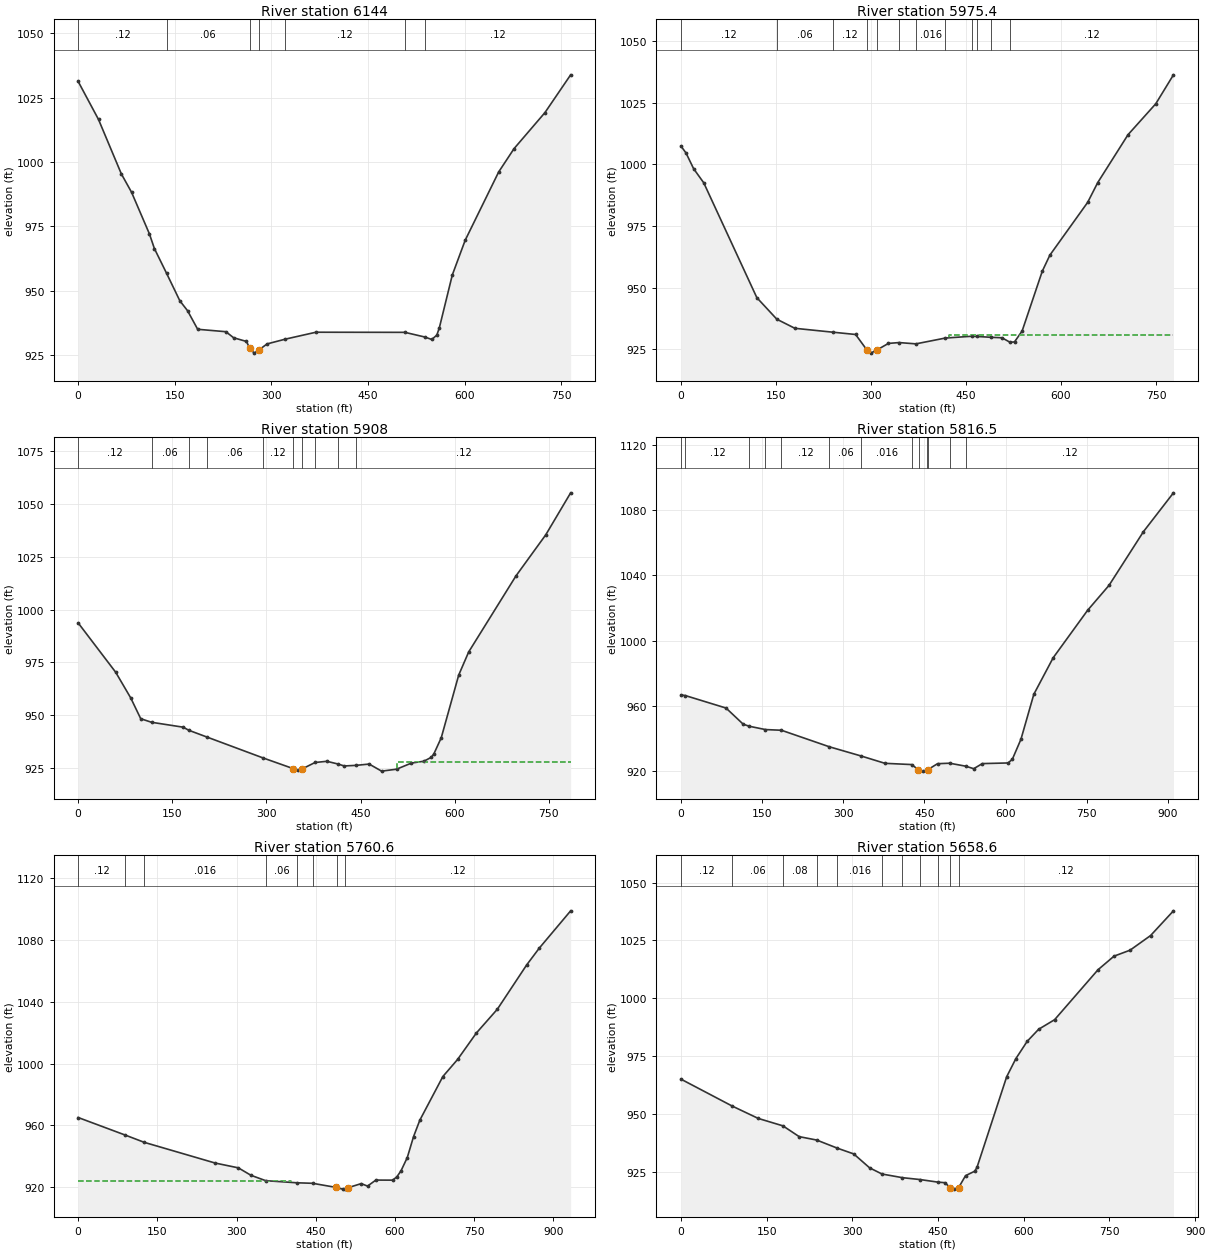
Type RM Length L Ch R = 1 ,6144    ,177.7,168.5,159.1
XS GIS Cut Line= 4
     1751600.474      395781.847     1751557.071      395966.308
     1751662.323      396305.935     1751627.601      396522.949
#Sta/Elev= 30
       0 1031.32    31.6 1016.56    67.1   995.4    82.9   988.3   110.5  972.22
   118.4  966.42  137.39956.7736   157.9  946.14   169.8  942.32   185.6  935.08
   229.4  934.14   241.4  931.79   261.4  930.35   266.3   927.7   273.4  925.82
   281.3  927.18   293.4   929.4  321.92931.2646   369.3  933.94  507.45933.8906
  538.37932.0746   549.1  931.12     557  932.82     561  935.77     581  956.16
     601  969.65     653  996.17   676.9 1005.24   724.9 1019.24   764.8  1033.9
#Mann= 7 ,-1 , 0
       0     .12       0  137.39     .06       0   266.3    .045       0
   281.3    .016       0  321.92     .12       0  507.45    .016       0
  538.37     .12       0
Bank Sta=266.3,281.3
XS Rating Curve= 0 ,0
Exp/Cntr=0.3,0.1

Type RM Length L Ch R = 1 ,5975.4  ,71.1,67.4,64
XS GIS Cut Line= 4
     1751409.502      395793.782     1751404.077       396069.39
     1751523.434      396213.704     1751559.242      396526.204
#Sta/Elev= 30
       0 1007.42       8 1004.61      20  998.24      36  992.51   119.8  945.95
  151.37937.2107   179.8  933.53  239.99931.9426   275.7  931.02  293.73924.6691
   299.6  923.46  309.09924.7044   327.5   927.4  344.36927.7412  370.94927.2183
  417.28929.5726  459.35930.3081  466.79 930.215  489.88  929.88   506.7  929.69
  519.61927.8536   526.6  928.02   538.6  932.43   570.4  956.67   582.4  963.19
   642.1  984.61     658  992.63   705.8 1012.04   749.6 1024.58   777.5 1036.31
#Mann= 12 ,-1 , 0
       0     .12       0  151.37     .06       0  239.99     .12       0
  293.73    .045       0  309.09     .12       0  344.36     .06       0
  370.94    .016       0  417.28     .06       0  459.35    .016       0
  466.79     .12       0  489.88    .016       0  519.61     .12       0
#XS Ineff= 2 , 0
                           422.7          930.74
Permanent Ineff=
       F       F
Bank Sta=293.73,309.09
XS Rating Curve= 0 ,0
Exp/Cntr=0.3,0.1

Type RM Length L Ch R = 1 ,5908    ,113,91.5,70.5
XS GIS Cut Line= 4
     1751337.882      395798.553     1751337.882      396105.628
     1751405.156      396164.221     1751411.666      396552.676
#Sta/Elev= 30
       0  993.68    59.8   970.3    83.8   958.1    99.7  948.27  117.03946.5778
   167.5  944.25   176.1942.8185  205.64  939.54  294.25929.7269   342.3  924.66
   349.7   923.8   357.3  924.54  377.48927.5195   396.3  928.09  413.47926.8419
     424  925.88  443.01926.1656   463.7  926.78   483.5  923.43   507.3  924.34
   531.1  927.25   550.9  928.12   562.8     930   566.8  931.58   578.6  939.26
   606.4  968.96   622.3  979.92   697.6 1015.94   745.2 1035.47   784.8 1055.34
#Mann= 10 ,-1 , 0
       0     .12       0  117.03     .06       0   176.1     .12       0
  205.64     .06       0  294.25     .12       0   342.3    .045       0
   357.3     .12       0  377.48     .06       0  413.47    .016       0
  443.01     .12       0
#XS Ineff= 2 , 0
                          508.57           927.8
Permanent Ineff=
       F       F
Bank Sta=342.3,357.3
XS Rating Curve= 0 ,0
Exp/Cntr=0.3,0.1

Type RM Length L Ch R = 1 ,5816.5  ,61,56,56
XS GIS Cut Line= 4
     1751263.061      395789.138     1751281.768      396209.277
      1751350.37      396203.666     1751349.111      396624.412
#Sta/Elev= 30
       0  966.79    8.31966.3544    83.3  958.73   115.1  948.82  126.57947.5647
  156.14945.5564   185.7 945.138   274.4935.0023  333.53929.3246   376.9   924.9
   426.4924.1347  438.24   921.1   439.7  920.75   447.3  920.12     455  920.75
  456.03920.9858   474.1  924.67  496.66924.9631   526.2 923.142     541  921.61
   556.9  924.73   604.5  925.12   612.4  927.39   628.3  939.64   652.1  967.18
   687.8   989.5   751.4 1018.54   791.1 1033.86   854.6 1066.69   910.1 1090.47
#Mann= 13 ,-1 , 0
       0     .08       0    8.31     .12       0  126.57     .06       0
  156.14     .08       0   185.7     .12       0   274.4     .06       0
  333.53    .016       0   426.4     .06       0   439.7    .045       0
     455     .06       0  456.03     .12       0  496.66    .016       0
   526.2     .12       0
Bank Sta=438.24,456.03
XS Rating Curve= 0 ,0
Exp/Cntr=0.3,0.1

Type RM Length L Ch R = 1 ,5760.6  ,48.6,102,149.9
XS GIS Cut Line= 4
     1751223.055      395797.003     1751242.879      396251.465
     1751323.981      396248.284     1751322.691      396644.907
#Sta/Elev= 30
       0  965.11   89.13953.7538  125.23949.0423   259.4  935.66   303.3  932.55
   327.2  927.74  355.21924.2431  414.33922.8818   443.9922.5525  487.95  919.92
   489.7  919.66   501.3  918.78   505.1  918.88  510.08   919.6   536.1  922.35
     548  920.74   563.8  924.63   595.6  924.59   603.5  926.72   611.4   930.6
   623.3  939.22   635.2  952.78   647.1  963.42   690.7  991.64   718.5 1002.65
   754.2 1019.81   793.9 1035.19   849.4 1063.83   873.2 1074.67   932.7 1098.83
#Mann= 8 ,-1 , 0
       0     .12       0   89.13     .06       0  125.23    .016       0
  355.21     .06       0  414.33    .016       0   443.9     .12       0
   489.7    .045       0   505.1     .12       0
#XS Ineff= 2 , 0
          403.51  924.32
Permanent Ineff=
       F       F
Bank Sta=487.95,510.08
XS Rating Curve= 0 ,0
Exp/Cntr=0.3,0.1

Type RM Length L Ch R = 1 ,5658.6  ,241.4,234.1,226.4
XS GIS Cut Line= 3
     1751216.354      395796.383     1751231.545       396138.18
     1751068.784      396631.886
#Sta/Elev= 30
       0     965   89.76953.3579   135.3  948.02  178.45 944.813   206.9  940.15
  237.58938.6744   273.9935.1495   302.4  932.68   330.2  926.66  351.81923.9975
  387.65922.4097  418.75921.5927  449.85920.4806   462.1  920.24  471.58918.0047
   478.1  917.46   486.1  918.16   498.1  923.28   514.1   925.2   518.1  926.82
   570.1  966.04   586.1  973.84     606  981.35     626  986.55     654   990.7
     730  1012.3     758 1018.17     786 1020.74     822 1027.08     862 1037.76
#Mann= 11 ,-1 , 0
       0     .12       0   89.76     .06       0  178.45     .08       0
  237.58     .12       0   273.9    .016       0  351.81     .06       0
  387.65     .12       0  418.75    .016       0  449.85     .12       0
  471.58    .045       0   486.1     .12       0
Bank Sta=471.58,486.1
XS Rating Curve= 0 ,0
Exp/Cntr=0.3,0.1

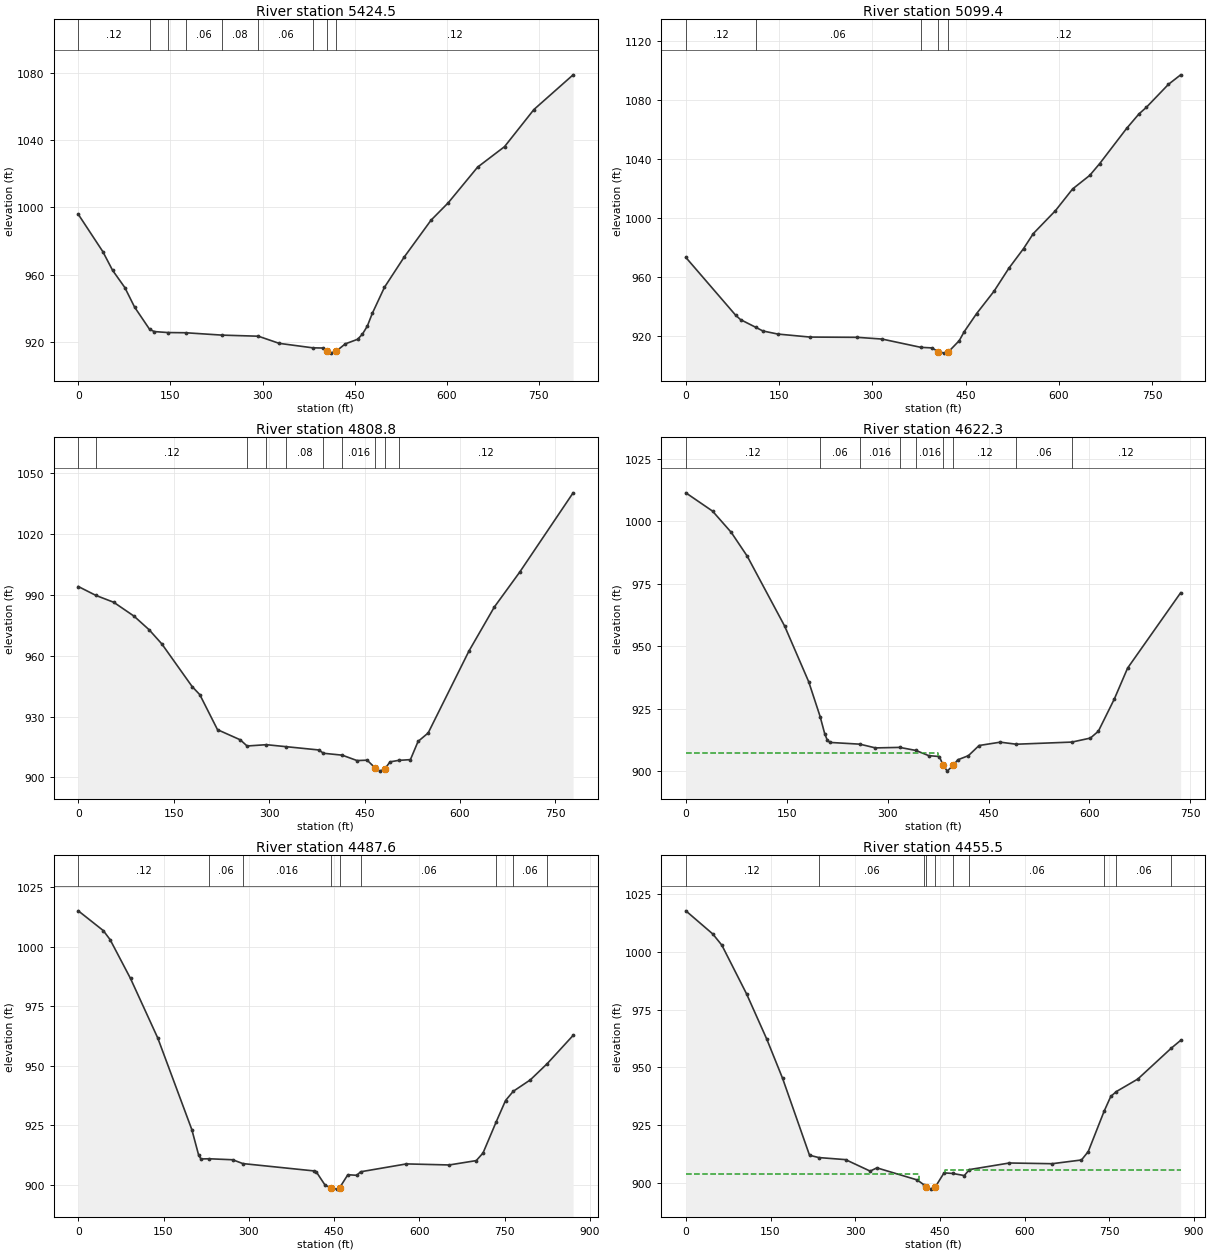
Type RM Length L Ch R = 1 ,5424.5  ,324.7,325.1,325.4
XS GIS Cut Line= 2
     1750958.107      395799.638     1750968.356      396605.197
#Sta/Elev= 30
       0  995.94    39.9  973.85    55.8  962.76    75.8  952.49    91.7  940.89
  115.96927.8033   123.6  926.41   145.5925.8285  175.04925.7004  234.11924.2949
  293.19 923.651     327  919.42   381.8916.7585   398.8  916.65   405.1  914.72
   410.8  913.62   420.1  914.82   434.7  919.11   454.7  921.82   462.6  924.87
   470.6  929.68   478.6  937.14   498.5  952.68   530.4  970.49   574.3  992.46
   602.2 1002.73   650.1 1023.91     694 1036.08   741.8 1058.08   805.6 1078.65
#Mann= 9 ,-1 , 0
       0     .12       0  115.96     .06       0   145.5     .12       0
  175.04     .06       0  234.11     .08       0  293.19     .06       0
   381.8    .016       0   405.1    .045       0   420.1     .12       0
Bank Sta=405.1,420.1
XS Rating Curve= 0 ,0
Exp/Cntr=0.3,0.1

Type RM Length L Ch R = 1 ,5099.4  ,290.2,290.6,290.8
XS GIS Cut Line= 3
     1750639.875      395803.463     1750639.478      396299.208
      1750710.11      396591.091
#Sta/Elev= 30
       0  973.42      80  934.37      88  931.32  112.13926.1937   123.9  923.65
   147.9  921.56   199.9  919.51   275.9  919.34   315.8  918.16  377.95912.5686
   395.8  912.19  406.11909.6718   415.8  908.65  421.62909.1877   439.8  917.09
   447.8  923.16   467.8  935.45   495.8  950.57   519.4  965.96   543.2  979.36
     559  989.58   594.5 1005.03   622.2 1019.77   649.8 1028.96   665.7 1036.89
   709.1 1060.75   728.9 1070.52   740.7 1074.94   776.3 1090.53     796 1096.98
#Mann= 5 ,-1 , 0
       0     .12       0  112.13     .06       0  377.95    .016       0
  406.11    .045       0  421.62     .12       0
Bank Sta=406.11,421.62
XS Rating Curve= 0 ,0
Exp/Cntr=0.3,0.1

Type RM Length L Ch R = 1 ,4808.8  ,172.4,186.5,200.6
XS GIS Cut Line= 3
     1750277.167      395775.119       1750352.5      396104.807
     1750345.989       396544.26
#Sta/Elev= 30
       0  994.22   27.85989.8014    55.7  986.44    87.5  979.62   111.4  972.86
   131.3  965.89     179  944.82     191  940.84   218.8  923.57   254.6  918.56
  265.29915.5102  295.59  916.16  325.88915.1997   378.1  913.55  385.27911.9321
  414.81910.9887   438.1  908.32     454  908.51   466.9  904.58     474  903.11
   481.9  904.29     490  907.69  503.42908.4096     522  908.79     534  917.76
   549.9  921.95   613.9  962.33   653.8  984.06   693.8 1001.34   777.7 1040.45
#Mann= 10 ,-1 , 0
       0     .06       0   27.85     .12       0  265.29    .016       0
  295.59     .06       0  325.88     .08       0  385.27     .12       0
  414.81    .016       0   466.9    .045       0   481.9     .06       0
  503.42     .12       0
Bank Sta=466.9,481.9
XS Rating Curve= 0 ,0
Exp/Cntr=0.3,0.1

Type RM Length L Ch R = 1 ,4622.3  ,93.3,134.7,158.4
XS GIS Cut Line= 4
     1750220.121      395775.307     1750236.397      396096.488
     1750086.658      396299.396     1750079.062      396461.071
#Sta/Elev= 30
       0 1011.44    39.7 1004.12    67.5   995.6    91.3  986.05   146.9  958.06
   182.6  935.81  199.62921.8508   206.4  915.01   210.4   912.3   214.4  911.47
  258.77910.7766   281.9  909.28  317.92909.4872  341.95 908.265     361  906.19
   376.8  905.83  382.53 902.338   388.6  899.98  397.76902.4398   404.3  904.51
   420.1  906.18   435.9  910.24   467.4  911.58  491.17910.7579  573.94 911.614
   601.4  913.22   613.2  915.95   636.9  928.83   656.7  941.24   735.6  971.43
#Mann= 9 ,-1 , 0
       0     .12       0  199.62     .06       0  258.77    .016       0
  317.92     .12       0  341.95    .016       0  382.53    .045       0
  397.76     .12       0  491.17     .06       0  573.94     .12       0
#XS Ineff= 2 , 0
          374.82  907.43
Permanent Ineff=
       F       F
Bank Sta=382.53,397.76
XS Rating Curve= 0 ,0
Exp/Cntr=0.3,0.1

Type RM Length L Ch R = 1 ,4487.6  ,50.5,32.1,30.8
XS GIS Cut Line= 4
     1750201.485      395774.222     1750219.405      396085.463
     1750041.019      396086.331     1749986.641      396463.024
#Sta/Elev= 30
       0 1014.98      44 1006.69      56 1002.89    91.9  986.59   139.9  961.59
   199.8  923.19   211.8  912.49   215.8  910.88  230.37910.9557   271.8  910.54
  289.54908.9387   414.8  905.86   418.8  905.46   434.6  899.77   444.9  898.85
   454.5  898.22   459.9  898.82   474.3  904.26   490.1  904.02   496.7905.4965
   577.4   908.8   652.7  908.36   700.3  910.19   712.2  913.39  735.44926.4898
   751.8  935.39  765.28939.2452   795.4  944.06  824.96950.8246   870.7  962.72
#Mann= 9 ,-1 , 0
       0     .12       0  230.37     .06       0  289.54    .016       0
   444.9    .045       0   459.9    .016       0   496.7     .06       0
  735.44     .12       0  765.28     .06       0  824.96     .12       0
Bank Sta=444.9,459.9
XS Rating Curve= 0 ,0
Exp/Cntr=0.3,0.1

Type RM Length L Ch R = 1 ,4455.5  ,162.1,124.4,87
XS GIS Cut Line= 4
     1750190.759      395768.927     1750207.686      396059.292
     1750029.301       396060.16     1749972.009      396463.371
#Sta/Elev= 30
       0 1017.88    47.8 1007.82    63.8 1002.97   107.6  981.83   143.4  962.19
   171.3  945.24   219.1  911.83  235.68910.8197   282.9  909.93   326.5  904.95
   338.4  906.36   409.8  901.12  421.92898.9736   425.6  898.03   433.6  897.13
   441.5  897.94   457.4  904.19   472.4 903.938   493.2  903.02  502.24905.6064
   573.1  908.47   648.9  908.16   700.8  909.78   712.8  913.44  740.89930.9254
   752.7  937.36  762.65 939.475   800.6   944.9  860.22958.3742   876.5  961.68
#Mann= 10 ,-1 , 0
       0     .12       0  235.68     .06       0  421.92     .12       0
   425.6    .045       0   441.5     .12       0   472.4    .016       0
  502.24     .06       0  740.89     .12       0  762.65     .06       0
  860.22     .12       0
#XS Ineff= 2 , 0
          413.28  903.81  459.24          905.54
Permanent Ineff=
       F       F
Bank Sta=425.6,441.5
XS Rating Curve= 0 ,0
Exp/Cntr=0.3,0.1

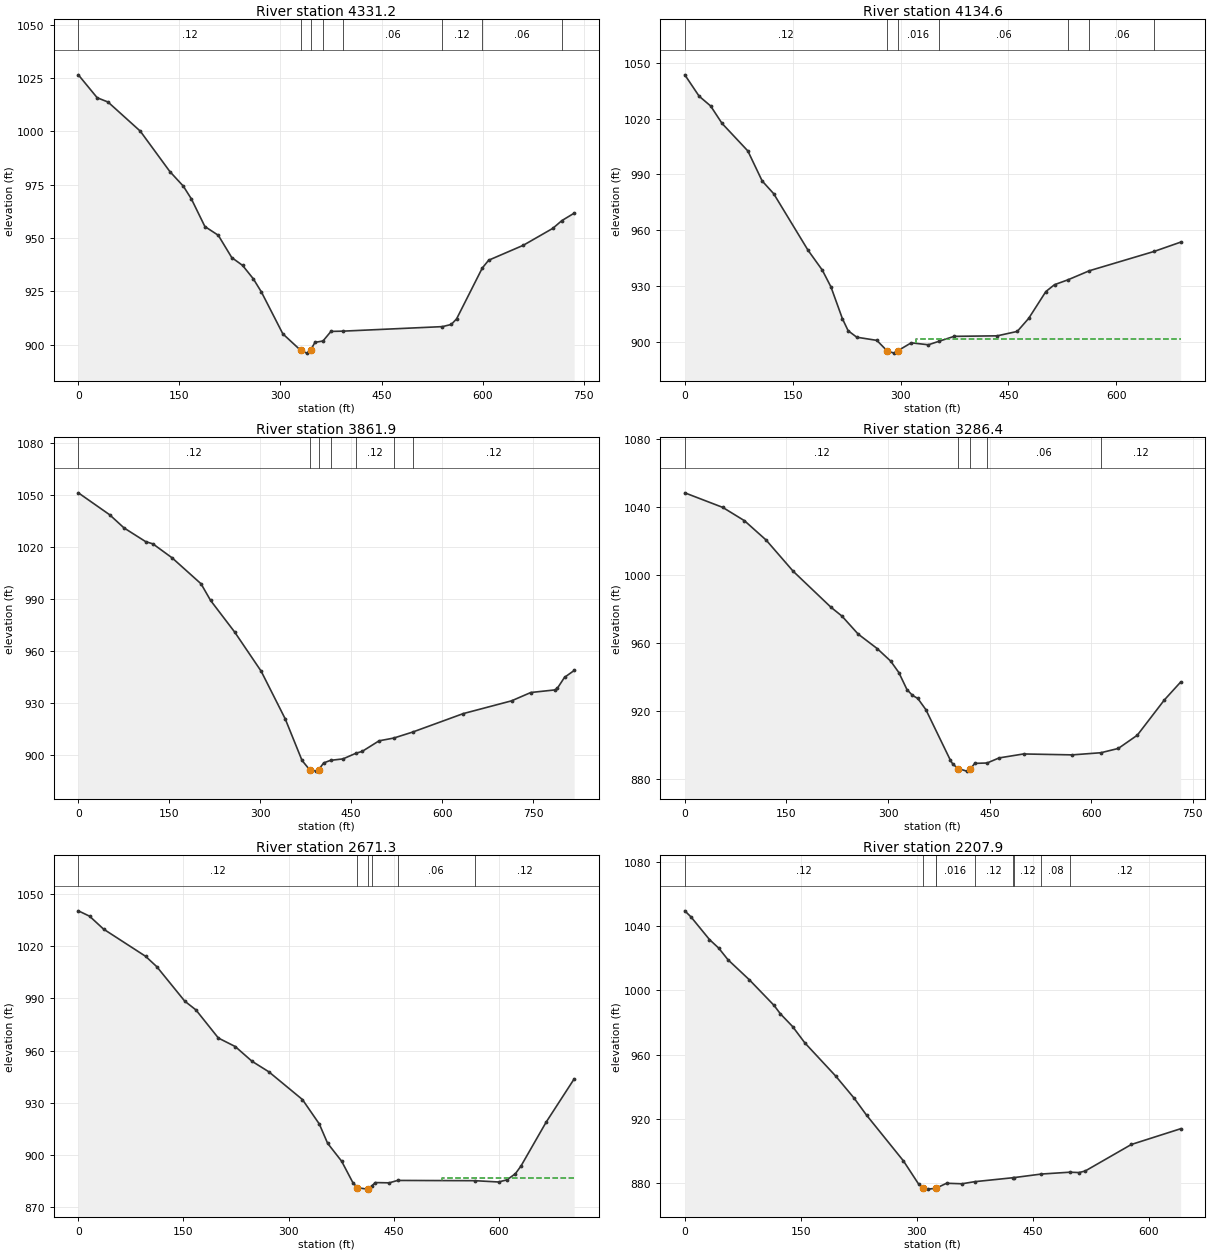
Type RM Length L Ch R = 1 ,4331.2  ,199.9,196.6,193
XS GIS Cut Line= 3
     1749763.929      395800.076     1749953.816       396021.43
     1749966.215      396465.411
#Sta/Elev= 30
       0 1026.44      28 1015.69      44  1013.7    91.9 1000.06   135.8  981.12
   155.8  974.27   167.8  968.27   187.8  955.35   207.7  951.24   227.7  940.79
   243.7  937.14   259.7  930.84   271.7  924.66   303.5  905.05   330.2  897.26
   339.2  896.02   345.2  897.68   351.1  901.06  363.06901.6999   374.9  906.19
  392.61 906.319  540.34 908.442   553.4  909.46   561.3  912.05  599.44935.8908
   608.9  939.56   660.4  946.57   704.1  954.49  717.63958.1437   735.8   961.6
#Mann= 8 ,-1 , 0
       0     .12       0   330.2    .045       0   345.2    .016       0
  363.06     .12       0  392.61     .06       0  540.34     .12       0
  599.44     .06       0  717.63     .12       0
Bank Sta=330.2,345.2
XS Rating Curve= 0 ,0
Exp/Cntr=0.3,0.1

Type RM Length L Ch R = 1 ,4134.6  ,284.6,272.6,260.6
XS GIS Cut Line= 2
     1749713.698      395803.244     1749824.809        396483.8
#Sta/Elev= 30
       0 1043.55    19.9 1032.07    35.9 1026.81    51.8 1017.42    87.7  1002.6
   107.6  986.46   123.6  979.62   171.4  949.18   191.3  938.47   203.3  929.44
   219.2  912.37   227.2  905.88   239.2   902.4   267.1   900.7  281.27895.1019
     291  893.84  295.98895.0629   314.9  899.38   338.8  898.33  353.27900.1896
   374.7  902.87   434.5  903.14   462.4  905.52   478.3  912.54   502.2  926.98
   514.2  930.66  532.83933.2668  562.76 938.172  652.54948.5221   689.6  953.54
#Mann= 7 ,-1 , 0
       0     .12       0  281.27    .045       0  295.98    .016       0
  353.27     .06       0  532.83     .12       0  562.76     .06       0
  652.54     .12       0
#XS Ineff= 2 , 0
                          321.47          901.59
Permanent Ineff=
       F       F
Bank Sta=281.27,295.98
XS Rating Curve= 0 ,0
Exp/Cntr=0.3,0.1

Type RM Length L Ch R = 1 ,3861.9  ,571.2,575.5,579.6
XS GIS Cut Line= 3
     1749253.107      395855.024     1749540.868       396209.19
     1749652.847       396552.94
#Sta/Elev= 30
       0 1051.29    51.6 1038.63    75.4 1030.99   111.1 1023.07     123 1021.79
   154.8 1013.67   202.4  998.71   218.2  989.06   257.9   970.8   301.6  948.17
   341.3   920.6     369  896.59   381.4  891.28   392.8  890.41   396.4  891.29
   404.8  895.17  416.03 896.643   436.5  897.47  458.21900.7868   468.2  901.81
   496.1  907.93  520.33909.5294   551.4 912.982   635.1  923.68   714.6  931.04
   746.4  935.86   786.1  937.36     790  938.21     802  944.62   817.9  948.59
#Mann= 7 ,-1 , 0
       0     .12       0   381.4    .045       0   396.4     .12       0
  416.03    .016       0  458.21     .12       0  520.33     .06       0
   551.4     .12       0
Bank Sta=381.4,396.4
XS Rating Curve= 0 ,0
Exp/Cntr=0.3,0.1

Type RM Length L Ch R = 1 ,3286.4  ,618.2,615.1,611.8
XS GIS Cut Line= 2
     1748808.769      396084.612     1749157.727      396727.841
#Sta/Elev= 30
       0 1048.38      56 1039.82      88 1032.01     120 1020.64     160 1002.28
   215.9  981.08   231.9  975.96   255.9  965.36   283.9  956.88   303.9  949.47
   315.9  942.78   327.9  932.76   335.9  929.41   343.9  927.54   355.9  920.91
   391.9  891.33   395.9  888.74   403.9  886.35   415.9  884.84  421.61 886.176
   427.9  889.39  446.19 889.623   463.9   892.6   499.9  894.93   571.8  894.39
  614.19895.6535   639.8  898.17   667.8  905.93   707.8  926.67   731.8  937.17
#Mann= 5 ,-1 , 0
       0     .12       0   403.9    .045       0  421.61    .016       0
  446.19     .06       0  614.19     .12       0
Bank Sta=403.9,421.61
XS Rating Curve= 0 ,0
Exp/Cntr=0.3,0.1

Type RM Length L Ch R = 1 ,2671.3  ,462.7,463.4,463.3
XS GIS Cut Line= 2
     1748237.154      396436.175     1748659.029      397003.883
#Sta/Elev= 30
       0 1040.16      16 1037.09      36 1029.67    95.9 1014.08   111.9 1008.12
   151.8  988.34   167.8  983.28   199.8  967.15   223.8  962.29   247.8  953.82
   271.7   947.8   319.7  931.86   343.7  917.88   355.6  906.78   375.6  896.48
   391.6  884.21     398  881.32   411.6  880.46     413  880.69  418.61 882.314
   423.6  884.22   443.6  884.07   455.4 885.447   565.8 885.302   599.4  884.56
   611.4  885.78   623.4  889.28   631.4  893.69   667.3  918.87   707.3   943.7
#Mann= 6 ,-1 , 0
       0     .12       0     398    .045       0     413     .12       0
  418.61    .016       0   455.4     .06       0   565.8     .12       0
#XS Ineff= 2 , 0
                           519.3          886.69
Permanent Ineff=
       F       F
Bank Sta=398,413
XS Rating Curve= 0 ,0
Exp/Cntr=0.3,0.1

Type RM Length L Ch R = 1 ,2207.9  ,472.7,485.3,497.8
XS GIS Cut Line= 2
     1747906.425      396753.883     1748284.029      397272.112
#Sta/Elev= 30
       0 1049.64       8 1045.85    31.9 1031.73    43.8 1026.43    55.8 1019.16
    83.6 1006.57   115.5  990.63   123.5  985.46   139.4  977.48   155.3  967.25
   195.2  946.56     219  932.79     235  922.23   282.8  893.64   302.7  878.98
  308.67876.8928   314.6  876.07  324.56876.5787  324.91876.6339   338.5  879.73
   358.4  879.41  375.07880.7236  424.62883.1927  425.22883.2281  461.16885.4801
  497.71 886.622   509.8  886.41   517.7  887.35   577.5  903.92   641.2  913.73
#Mann= 9 ,-1 , 0
       0     .12       0  308.67    .045       0  324.56     .06       0
  324.91    .016       0  375.07     .12       0  424.62     .06       0
  425.22     .12       0  461.16     .08       0  497.71     .12       0
Bank Sta=308.67,324.56
XS Rating Curve= 0 ,0
Exp/Cntr=0.3,0.1

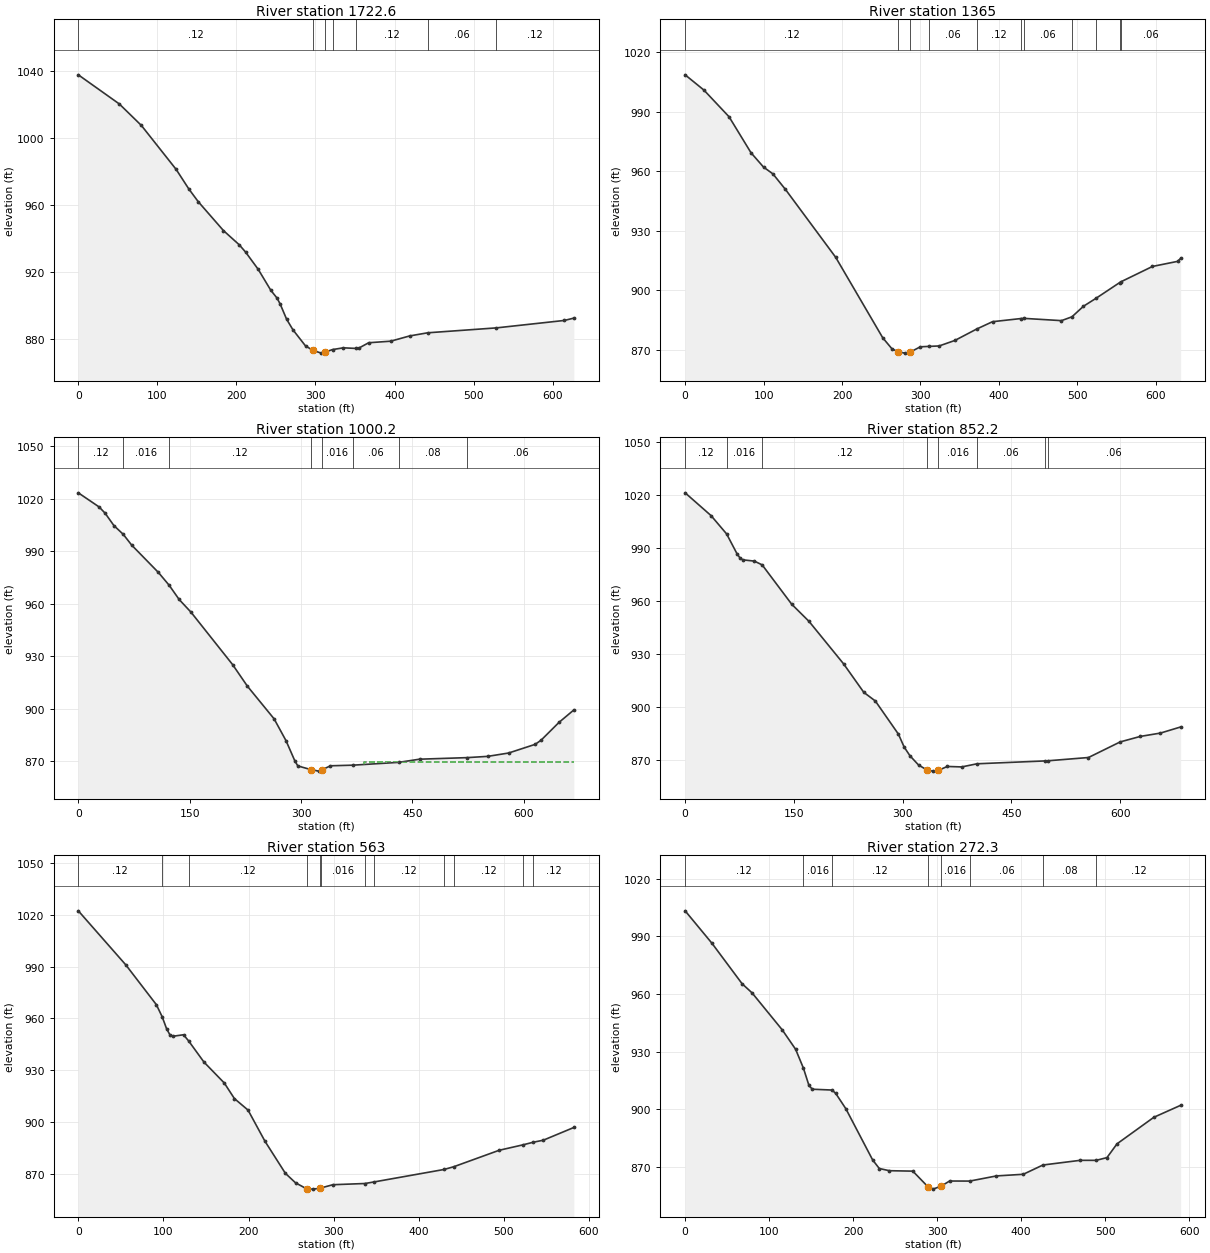
Type RM Length L Ch R = 1 ,1722.6  ,361.1,357.6,353.9
XS GIS Cut Line= 2
     1747651.216      396894.508     1747698.091      397519.508
#Sta/Elev= 30
       0 1037.75    51.9 1020.32    79.8 1007.46   123.8  981.17   139.7  969.56
   151.7  961.89   183.6  944.61   203.6   936.1   211.6  931.75   227.6  921.41
   243.5  908.91   251.5  904.17   255.5  900.52   263.5   891.6   271.5  885.27
   287.4  875.65   297.1  872.91   307.4  871.33   312.1  871.94  321.61873.4618
   335.3   874.5  351.22874.1434   355.3  874.45   367.3  877.54   395.2  878.47
   419.2  881.62  441.98883.4896  528.94886.4303   614.8  890.87   626.8  892.26
#Mann= 7 ,-1 , 0
       0     .12       0   297.1    .045       0   312.1     .12       0
  321.61    .016       0  351.22     .12       0  441.98     .06       0
  528.94     .12       0
Bank Sta=297.1,312.1
XS Rating Curve= 0 ,0
Exp/Cntr=0.3,0.1

Type RM Length L Ch R = 1 ,1365    ,365.9,364.8,363.3
XS GIS Cut Line= 2
     1747260.591      397001.279     1747406.425      397615.862
#Sta/Elev= 30
       0 1008.65      24 1000.94      56  987.49      84  969.34    99.9  962.14
   111.9   958.7   127.9  950.85   191.9  916.64   251.9  876.04   263.8  870.41
   271.4  869.09   279.8  868.32   286.4  868.74   299.8  871.51  310.95  871.72
   323.8  871.94   343.8  874.71  371.66880.4753   391.8  884.17   427.9885.7518
  432.37885.8342   479.7   884.7  493.08 886.636   507.7  891.95  523.44895.8855
  553.79903.8664  555.83904.3535   595.7  912.03   627.6  914.58   631.6  916.09
#Mann= 11 ,-1 , 0
       0     .12       0   271.4    .045       0   286.4    .016       0
  310.95     .06       0  371.66     .12       0   427.9     .08       0
  432.37     .06       0  493.08     .12       0  523.44     .06       0
  553.79     .12       0  555.83     .06       0
Bank Sta=271.4,286.4
XS Rating Curve= 0 ,0
Exp/Cntr=0.3,0.1

Type RM Length L Ch R = 1 ,1000.2  ,148.7,148,147.2
XS GIS Cut Line= 3
     1747041.841      397068.987     1746961.112      397324.195
     1747075.696      397707.008
#Sta/Elev= 30
       0 1023.44      28 1015.37      36 1011.85    47.9 1004.74   60.45999.7488
    71.9  993.55   107.9  977.91   122.4970.5815   135.8  962.48   151.8   955.2
   207.8  925.26   227.7  912.94   263.7  894.25   279.7   881.8   291.6  870.26
   295.6  867.36  313.65865.2112   323.6  864.39   327.6  865.04   339.6  867.44
  369.74867.7928   431.4 869.398   459.5  871.21  523.58872.1018   551.4  872.83
   579.4  874.73   615.3   879.7   623.3   882.1   647.3  892.23   667.3  899.35
#Mann= 8 ,-1 , 0
       0     .12       0   60.45    .016       0   122.4     .12       0
  313.65    .045       0   327.6    .016       0  369.74     .06       0
   431.4     .08       0  523.58     .06       0
#XS Ineff= 2 , 0
                          384.31          869.43
Permanent Ineff=
       F       F
Bank Sta=313.65,327.6
XS Rating Curve= 0 ,0
Exp/Cntr=0.3,0.1

Type RM Length L Ch R = 1 ,852.2   ,289.4,289.2,289.3
XS GIS Cut Line= 3
      1746609.55       397170.55     1746825.696      397381.487
     1746945.487      397743.466
#Sta/Elev= 30
       0 1021.36    35.8 1008.42   57.26998.0272    71.5  986.84    75.5  984.51
    79.5  983.36    95.4  982.65  106.26 980.492     147  958.18   170.9  948.44
   218.6  924.34   246.4  908.22   262.3  903.32   294.1  884.55     302  877.25
     310  872.28   321.9  867.02   333.8  864.15   341.7  863.56   348.8  863.94
   361.6  866.21   381.4  865.94  402.55867.7269  496.56869.3492  500.22869.4224
   556.2  871.28   599.9  880.12   627.7  883.24   655.5  885.14   683.3   888.6
#Mann= 8 ,-1 , 0
       0     .12       0   57.26    .016       0  106.26     .12       0
   333.8    .045       0   348.8    .016       0  402.55     .06       0
  496.56     .12       0  500.22     .06       0
Bank Sta=333.8,348.8
XS Rating Curve= 0 ,0
Exp/Cntr=0.3,0.1

Type RM Length L Ch R = 1 ,563     ,291.4,290.7,289.4
XS GIS Cut Line= 2
      1746484.55      397269.508     1746669.446      397821.591
#Sta/Elev= 30
       0  1022.2    55.8  990.97    91.7  967.98    98.5 961.031   103.7  954.09
   107.7   950.5   111.7  949.77   123.6   950.6  129.65947.0112   147.6  934.83
   171.5  922.73   183.4  913.73   199.4  907.08   219.3  889.08   243.3  870.54
   255.2  865.06   268.4  861.56   275.2  861.41   283.4  861.86  285.39862.1235
   299.1  863.96  336.66864.6536  347.68865.5785  429.67872.7626  441.13874.3452
   494.5  883.86  522.68 887.022  534.57 888.511   546.3  889.67   582.2  897.02
#Mann= 12 ,-1 , 0
       0     .12       0    98.5    .016       0  129.65     .12       0
   268.4    .045       0   283.4     .12       0  285.39    .016       0
  336.66     .06       0  347.68     .12       0  429.67     .06       0
  441.13     .12       0  522.68     .06       0  534.57     .12       0
Bank Sta=268.4,283.4
XS Rating Curve= 0 ,0
Exp/Cntr=0.3,0.1

Type RM Length L Ch R = 1 ,272.3   ,142.2,141,140
XS GIS Cut Line= 2
     1746203.498      397379.199     1746416.172      397929.329
#Sta/Elev= 30
       0 1003.21    31.9  986.35    67.8  965.28    79.7  960.52   115.6  941.28
   131.5  931.19  140.87921.2816   147.4  912.35   151.4  910.41  174.92 909.982
   179.3   908.2   191.3  900.26   223.2  873.62   231.1  869.17   243.1  868.02
     271   867.8   289.3  859.54   294.9  858.44   304.3  859.88   314.8  862.66
  338.74862.6272   370.6  865.31   402.5  866.16  425.86870.9839   470.2  873.42
  489.19873.4123   502.1  874.83   514.1  882.01   557.9  895.81   589.8  902.04
#Mann= 8 ,-1 , 0
       0     .12       0  140.87    .016       0  174.92     .12       0
   289.3    .045       0   304.3    .016       0  338.74     .06       0
  425.86     .08       0  489.19     .12       0
Bank Sta=289.3,304.3
XS Rating Curve= 0 ,0
Exp/Cntr=0.3,0.1

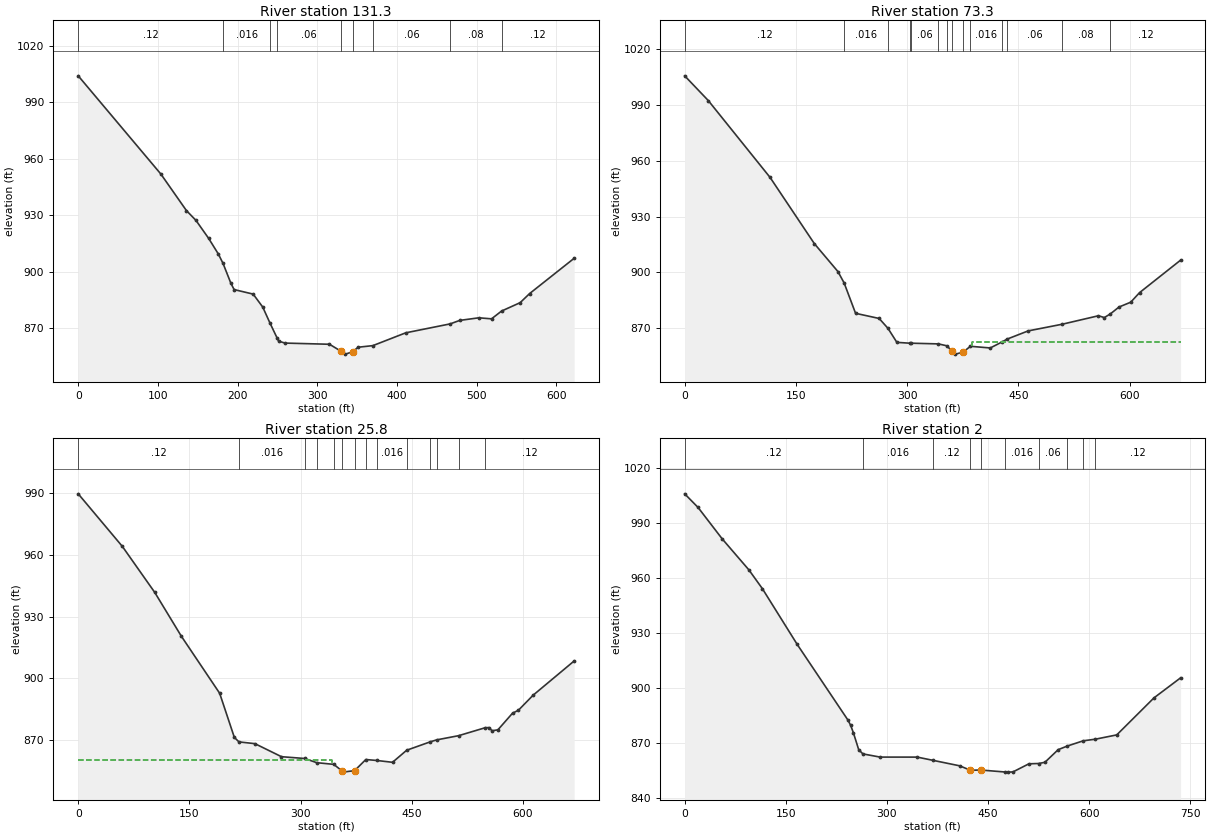
Type RM Length L Ch R = 1 ,131.3   ,67.2,58,47.9
XS GIS Cut Line= 3
     1746143.819       397387.88     1746146.008      397631.487
     1746299.654      397977.841
#Sta/Elev= 30
       0 1004.16   103.8  951.94   135.8  932.58   147.8  927.35   163.7  917.81
   175.7  909.62  181.79904.4939   191.7  893.87   195.7  890.59   219.6  888.18
   231.6  881.31  240.87  872.65  249.59864.9086   251.6  863.18   259.6  862.16
   315.4  861.53   329.4  857.95   335.4  856.29   344.4  857.53   351.3  859.95
  369.85860.8065   411.1  867.61  466.79872.3511   478.9  874.21   502.9  875.59
   518.8  875.04  531.41879.1838   554.7  883.63   566.7   888.5   622.5  907.21
#Mann= 9 ,-1 , 0
       0     .12       0  181.79    .016       0  240.87     .12       0
  249.59     .06       0   329.4    .045       0   344.4    .016       0
  369.85     .06       0  466.79     .08       0  531.41     .12       0
Bank Sta=329.4,344.4
XS Rating Curve= 0 ,0
Exp/Cntr=0.3,0.1

Type RM Length L Ch R = 1 ,73.3    ,47.5,47.5,48
XS GIS Cut Line= 4
     1746082.621       397384.19     1746089.566      397698.079
     1746218.732      397818.913     1746293.038      397980.718
#Sta/Elev= 30
       0 1005.77    31.8  992.48   115.2  951.09   174.9  915.47   206.7  900.45
  215.06894.3158   230.5  877.98   262.3  875.21  274.15869.9263   286.2  862.35
  303.69861.9026  304.72861.9104  342.16861.5283  354.13860.4508   360.3  857.45
   365.1  856.02   375.3  857.04   385.4860.2331   412.2  859.34  428.63862.7021
  435.02 864.128   463.3  868.52  509.08872.1003   558.1  876.67     566  875.69
  574.08877.6498   585.8  881.37   601.6  883.96   613.5   889.1   668.9   906.6
#Mann= 14 ,-1 , 0
       0     .12       0  215.06    .016       0  274.15     .12       0
  303.69    .016       0  304.72     .06       0  342.16    .016       0
  354.13     .08       0   360.3    .045       0   375.3     .08       0
   385.4    .016       0  428.63     .12       0  435.02     .06       0
  509.08     .08       0  574.08     .12       0
#XS Ineff= 2 , 0
                          387.93           862.5
Permanent Ineff=
       F       F
Bank Sta=360.3,375.3
XS Rating Curve= 0 ,0
Exp/Cntr=0.3,0.1

Type RM Length L Ch R = 1 ,25.8    ,18.3,23.8,29.4
XS GIS Cut Line= 4
     1746047.205      397411.968     1746054.149      397725.857
     1746183.316       397846.69     1746284.705      397993.218
#Sta/Elev= 30
       0   989.6    59.6  964.04   103.3  941.71   139.1  920.48   190.8  892.78
   210.6  871.36  216.82869.1702   238.4  868.31   274.2  861.98  305.45861.1136
  321.74859.0772  344.74858.2621  355.23855.2578   357.2  854.49   372.9  855.23
  387.97860.6073  402.63 860.152     424  859.26  443.08865.1184  474.44869.1418
  483.52870.1453  513.13872.1849  549.05876.0516   554.2  876.11   558.2  874.58
   566.1  875.01   585.9  883.11   593.8  884.53   613.6  891.82     669  908.46
#Mann= 14 ,-1 , 0
       0     .12       0  216.82    .016       0  305.45     .12       0
  321.74    .016       0  344.74     .12       0  355.23    .045       0
   372.9    .016       0  387.97     .12       0  402.63    .016       0
  443.08     .12       0  474.44     .06       0  483.52     .12       0
  513.13     .08       0  549.05     .12       0
#XS Ineff= 2 , 0
          341.69  860.27
Permanent Ineff=
       F       F
Bank Sta=355.23,372.9
XS Rating Curve= 0 ,0
Exp/Cntr=0.3,0.1

Type RM Length L Ch R = 1 ,2       ,5.7,2,0
XS GIS Cut Line= 4
     1746054.862      397373.675     1745981.946      397641.904
     1746121.884      397851.765     1746268.038      397995.996
#Sta/Elev= 30
       0 1006.14    19.8  998.72    55.6  981.56    95.3  964.58   115.2  954.37
   166.8  923.96   242.2  882.55   246.2  879.68   250.2  875.67   258.1  866.42
  264.32864.1221   289.8  862.38     345  862.37  368.64 860.577     408   857.6
   423.8  855.17   438.8  855.33  475.14854.2375     479  854.17   486.8  854.28
   510.5  858.71  524.82858.8808   534.2  859.53   553.9  866.44  567.51 868.426
  591.12871.2803     609872.1495   640.8   874.5     696  894.72   735.5  905.67
#Mann= 10 ,-1 , 0
       0     .12       0  264.32    .016       0  368.64     .12       0
   423.8    .045       0   438.8     .12       0  475.14    .016       0
  524.82     .06       0  567.51     .12       0  591.12     .06       0
     609     .12       0
Bank Sta=423.8,438.8
XS Rating Curve= 0 ,0
Exp/Cntr=0.3,0.1
LCMann Table=0

Chan Stop Cuts=-1
Use User Specified Reach Order=0
Composite Channel Slope=5